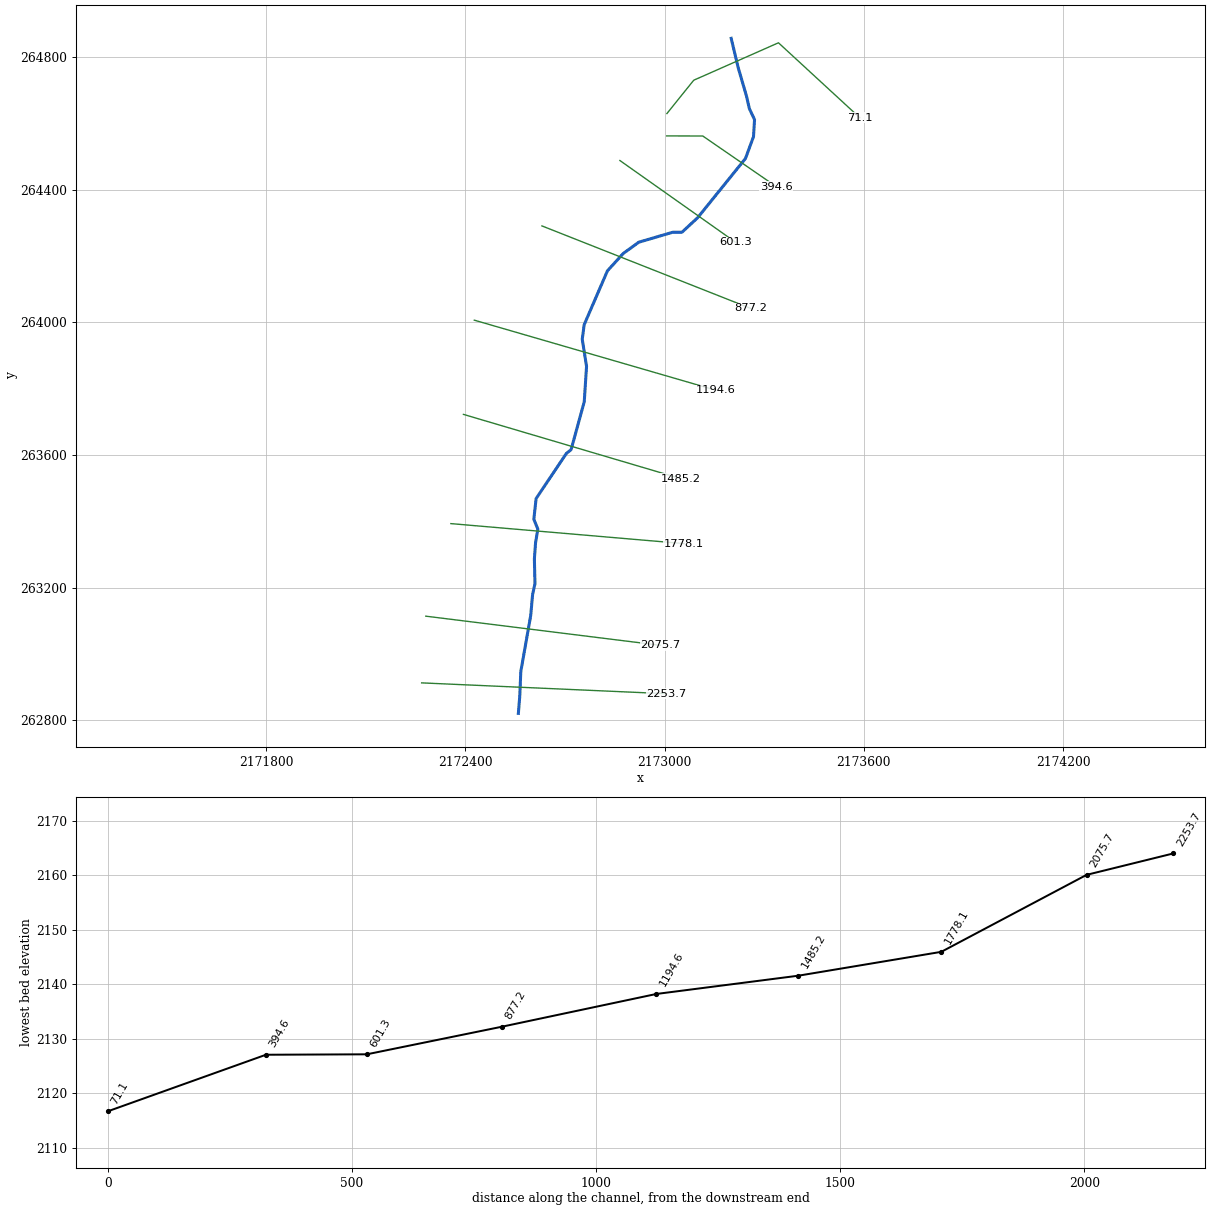
--- BroadRun.prj (project) ---

Proj Title=BroadRun
Current Plan=p01
Geom File=g01
Flow File=f01
Plan File=p01
DSS Export Rating Curves=0
DSS Export Rating Curve Sorted=0
DSS Export Volume Flow Curves=0
DXF OffsetX=0
DXF OffsetY=0
DXF ScaleX=0
DXF ScaleY=0

--- BroadRun.p01 (plan) ---

Plan Title=Floodplain
Program Version=4.00
Geom File=g01
Flow File=f01
K Sum by GR=0
Std Step Tol=0.01
Critical Tol=0.01
Num of Std Step Trials=20
Max Error Tol=0.3
Flow Tol Ratio=0.001
Split Flow NTrial=30
Split Flow Tol=0.02
Split Flow Ratio=0.02
Log Output Level=0
Friction Slope Method=1
Unsteady Friction Slope Method=2
Unsteady Bridges Friction Slope Method=1
Global Log Level=0
CheckData=False
Run HTab=0
Run UNet=0
Run PostProcess=0
UNET Theta=0
UNET Theta Warmup=0
UNET ZTol=0
UNET ZSATol=0
UNET MxIter=0
UNET MaxInSteps=0
UNET DtIC=0
UNET DtMin=0
UNET MaxCRTS=0
UNET WFStab=0
UNET SFStab=0
UNET WFX=0
UNET SFX=0
UNET DSS MLevel=0
UNET DZMax Abort=0
UNET Convert EG Bridges=0
UNET Use Existing IB Tables=0
UNET Froude Limit=0
UNET Froude Power=0
Write IC File=0
Echo Input=False
Echo Output=False
Write Detailed=0

--- BroadRun.f01 (steady flow) ---

Flow Title=NFF Regression Equation
Program Version=4.00
Number of Profiles=1
Profile Names=P100yr
River Rch & RM=BroadRun,Main      ,2253.7
588.3161
River Rch & RM=BroadRun,Main      ,71.1
602.2943
Boundary for River Rch & Prof#=BroadRun,Main      ,1
Up Type=0
Dn Type=3
Dn Slope=0.016254

--- BroadRun.g01 (geometry) ---

Geom Title=USGS 10m DEM
Program Version=4.10

River Reach=BroadRun        ,Main
Reach XY= 30
     2172559.999      262820.333      2172564.26      262872.888
     2172567.356      262946.635     2172597.242      263116.188
     2172602.892      263179.167     2172609.973      263211.426
     2172608.237      263286.078     2172611.709       263334.69
     2172618.654      263376.356     2172606.593      263405.839
      2172613.41      263468.466     2172704.227      263604.202
     2172718.749      263616.161      2172758.36      263760.531
      2172765.27      263867.345     2172752.334      263949.273
     2172758.157      263993.066     2172828.131      264155.527
     2172875.592      264207.855     2172922.444      264241.929
     2173025.274       264272.19     2173052.681       264272.19
     2173099.556      264315.592     2173243.654      264494.412
     2173267.959      264560.384     2173271.095      264611.877
     2173255.333      264645.435     2173247.126      264681.912
     2173221.809      264768.862      2173200.74      264857.115

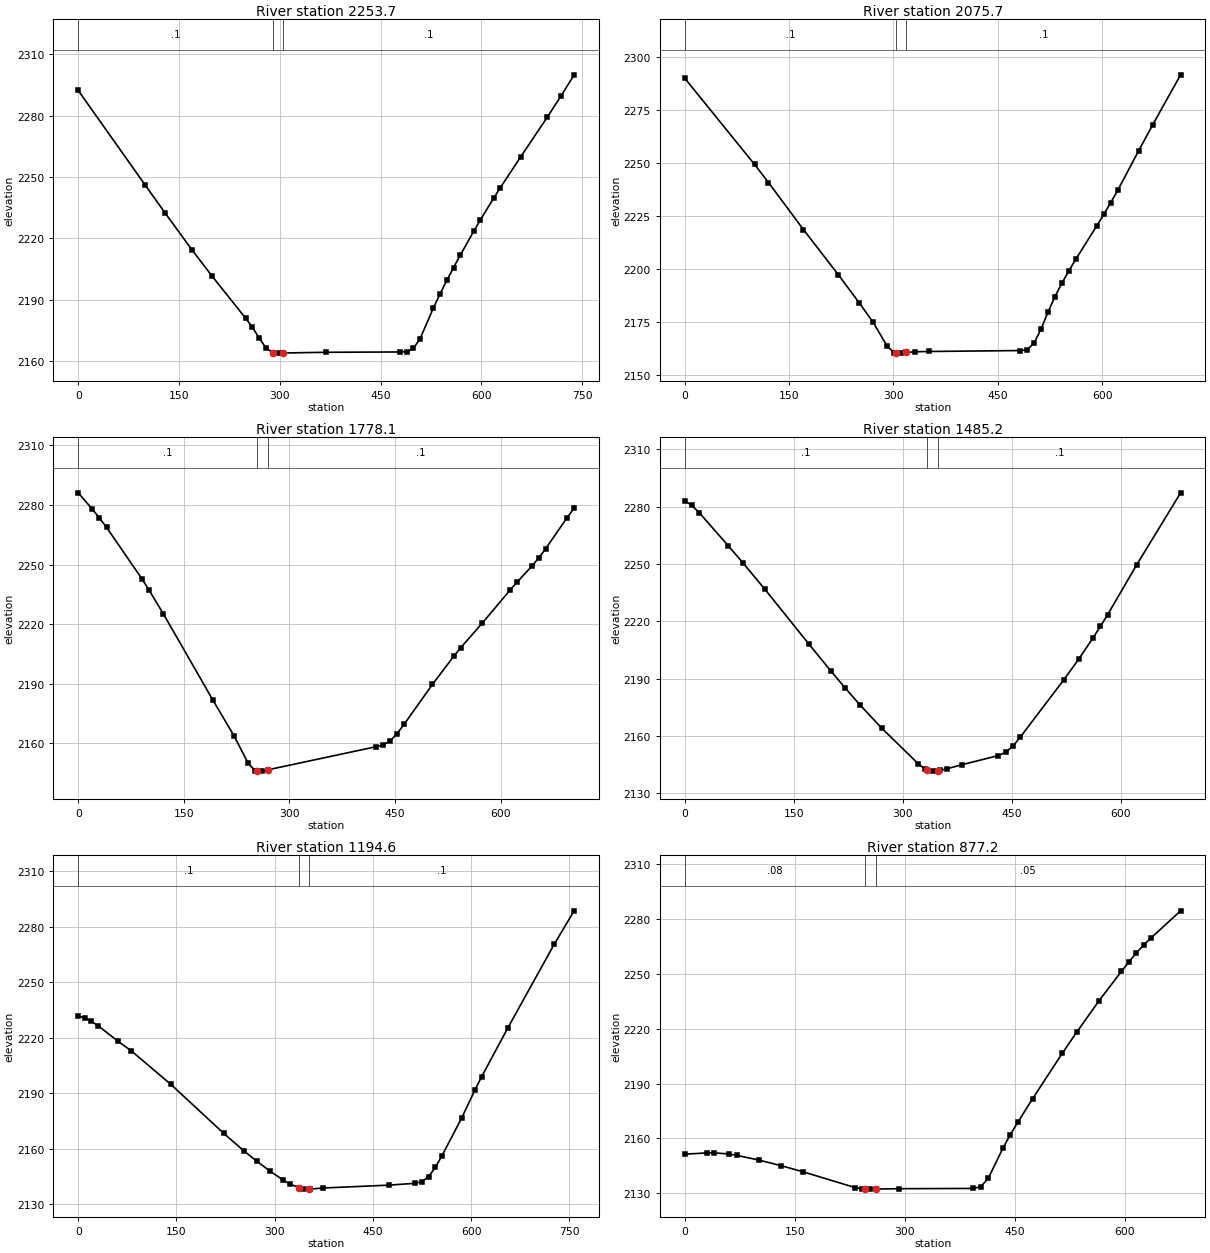
Type RM Length L Ch R = 1 ,2253.7  ,179.8,178,176.2
XS GIS Cut Line= 2
     2172268.772      262912.341     2173005.958      262879.633
#Sta/Elev= 30
       0 2292.27    99.7 2246.05   129.6 2232.31   169.5 2214.34   199.4 2201.54
   249.3 2180.99   259.3 2176.57   269.2 2171.45   279.2 2166.63   289.4 2164.28
   299.2 2164.04   304.4 2164.11     369 2164.45   478.6 2164.61   488.6 2164.76
   498.6 2166.31   508.6 2171.06   528.5  2186.1   538.5 2193.02   548.4 2199.53
   558.4 2205.76   568.4  2211.8   588.3 2223.43   598.3 2229.03   618.2 2239.71
   628.2 2244.85   658.1 2259.72     698 2279.25     718 2289.39   737.9 2299.88
#Mann= 3 , 0 , 0
       0      .1       0   289.4    .045       0   304.4      .1       0
Bank Sta=289.4,304.4
XS Rating Curve= 0 ,0
Exp/Cntr=0.3,0.1

Type RM Length L Ch R = 1 ,2075.7  ,296.7,297.6,298.5
XS GIS Cut Line= 2
     2172281.352       263113.62     2172988.346       263025.56
#Sta/Elev= 30
       0 2289.98   100.4 2249.23   120.4 2240.68   170.6 2218.46   220.8  2197.1
   250.9  2183.8   270.9 2174.58     291 2163.31     301 2160.36   303.5  2160.3
   311.1  2160.1   318.5  2160.4   331.1 2160.74   351.2 2160.88   481.7 2161.32
   491.7 2161.64   501.7 2164.72   511.8 2171.35   521.8 2179.33   531.8  2186.7
   541.9 2193.11   551.9 2198.93   561.9 2204.43     592 2220.21   602.1 2225.61
   612.1 2231.21   622.2 2237.04   652.2 2255.68   672.3  2267.9   712.5 2291.55
#Mann= 3 , 0 , 0
       0      .1       0   303.5    .045       0   318.5      .1       0
Bank Sta=303.5,318.5
XS Rating Curve= 0 ,0
Exp/Cntr=0.3,0.1

Type RM Length L Ch R = 1 ,1778.1  ,297.1,292.9,288.6
XS GIS Cut Line= 2
     2172356.832      263392.895     2173058.794      263332.511
#Sta/Elev= 30
       0 2286.13    20.1 2277.89    30.2 2273.45    40.3  2268.7    90.6  2242.8
   100.6 2237.16   120.8 2225.29   191.2 2181.82   221.4 2163.72   241.6 2149.83
   251.6 2146.14   254.3 2146.09   261.7 2145.97   269.3 2146.62   422.7 2158.23
   432.8 2159.14   442.9 2161.11   452.9 2164.78     463 2169.56   503.2  2189.6
   533.4 2203.74   543.5 2208.15   573.7 2220.35     614 2237.34     624 2241.38
   644.2 2249.07   654.2 2253.29   664.3 2258.09   694.5 2273.59   704.6 2278.42
#Mann= 3 , 0 , 0
       0      .1       0   254.3    .045       0   269.3      .1       0
Bank Sta=254.3,269.3
XS Rating Curve= 0 ,0
Exp/Cntr=0.3,0.1

Type RM Length L Ch R = 1 ,1485.2  ,291.1,290.6,290
XS GIS Cut Line= 2
     2172394.572       263722.49      2173048.73      263528.759
#Sta/Elev= 30
       0 2283.19      10 2280.71    20.1 2276.86    60.2 2259.47    80.3 2250.54
   110.4 2236.77   170.6 2208.25   200.7  2194.2   220.7 2185.16   240.8  2176.4
   270.9 2164.16   321.1 2145.51   331.1 2142.55   333.3 2142.34   341.1 2141.59
   348.3 2141.83   351.2 2141.92   361.2 2142.86   381.2 2144.94   431.4 2149.72
   441.4 2151.38   451.5 2154.63   461.5 2159.32   521.7 2189.51   541.8 2200.09
   561.8 2211.41   571.9 2217.36   581.9 2223.56     622 2249.77   682.2  2287.3
#Mann= 3 , 0 , 0
       0      .1       0   333.3    .045       0   348.3      .1       0
Bank Sta=333.3,348.3
XS Rating Curve= 0 ,0
Exp/Cntr=0.3,0.1

Type RM Length L Ch R = 1 ,1194.6  ,318.7,317.4,316.2
XS GIS Cut Line= 2
      2172427.28      264006.797     2173154.401      263795.454
#Sta/Elev= 30
       0 2231.65    10.1 2230.68    20.2 2228.79    30.3 2226.44    60.6 2218.12
    80.8 2212.96   141.4  2194.8   222.1 2168.35   252.4 2159.07   272.6 2153.31
   292.8 2147.98     313 2143.11   323.1 2141.01   337.4 2139.02   343.3 2138.45
   352.4 2138.26   353.4 2138.24   373.6 2138.84   474.5 2140.39   514.9  2141.4
     525 2142.28   535.1 2145.03   545.2 2149.97   555.3 2156.21   585.6 2176.75
   605.8 2191.82   615.9 2198.92   656.2 2225.44   726.9 2270.51   757.2 2288.47
#Mann= 3 , 0 , 0
       0      .1       0   337.4    .045       0   352.4      .1       0
Bank Sta=337.4,352.4
XS Rating Curve= 0 ,0
Exp/Cntr=0.3,0.1

Type RM Length L Ch R = 1 ,877.2   ,280.9,275.9,270.8
XS GIS Cut Line= 2
     2172631.075      264291.104     2173260.073      264042.021
#Sta/Elev= 30
       0 2151.35    30.3 2152.03    40.4 2152.09    60.6 2151.43    70.7 2150.75
     101 2148.14   131.3 2145.08   161.6 2141.69   232.2 2133.09   242.3 2132.41
   245.7 2132.34   252.4 2132.21   260.7 2132.26   292.8 2132.45   393.8 2132.59
   403.9 2133.53     414 2138.07   434.2  2154.7   444.3  2162.1   454.4 2168.83
   474.6 2181.72     515 2206.56   535.2 2218.39   565.4 2235.48   595.7 2251.41
   605.8 2256.59   615.9 2261.48     626 2265.81   636.1 2269.76   676.5  2284.6
#Mann= 3 , 0 , 0
       0     .08       0   245.7    .045       0   260.7     .05       0
Bank Sta=245.7,260.7
XS Rating Curve= 0 ,0
Exp/Cntr=0.3,0.1

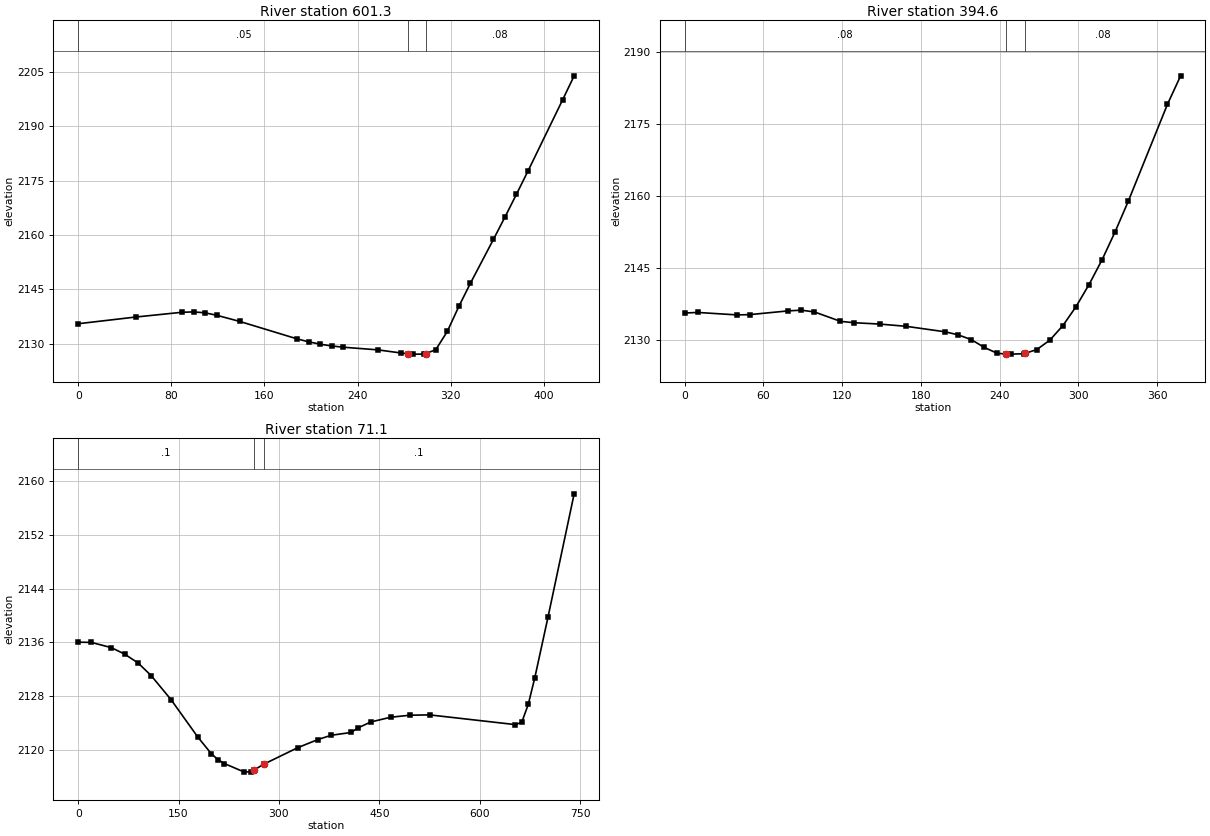
Type RM Length L Ch R = 1 ,601.3   ,206.4,206.7,207
XS GIS Cut Line= 2
     2172865.664      264488.486     2173213.393      264242.279
#Sta/Elev= 28
       0 2135.54    49.5 2137.39    89.2  2138.7    99.1  2138.8     109 2138.55
   118.9 2137.88   138.7 2136.18   188.3 2131.34   198.2 2130.54   208.1 2129.89
     218  2129.4   227.9 2129.06   257.6 2128.33   277.4 2127.47   283.7 2127.27
   287.4 2127.16   297.3 2127.16   298.7 2127.33   307.2 2128.38   317.1 2133.41
     327 2140.29   336.9 2146.66   356.7 2158.76   366.6 2164.92   376.5 2171.21
   386.4 2177.61   416.2 2197.27   426.1 2203.88
#Mann= 3 , 0 , 0
       0     .05       0   283.7    .045       0   298.7     .08       0
Bank Sta=283.7,298.7
XS Rating Curve= 0 ,0
Exp/Cntr=0.3,0.1

Type RM Length L Ch R = 1 ,394.6   ,300.3,323.5,347
XS GIS Cut Line= 3
      2173006.41      264562.653     2173115.186       264562.46
     2173336.683      264409.666
#Sta/Elev= 30
       0 2135.63     9.9 2135.75    39.6 2135.24    49.4 2135.29    79.1 2136.08
      89 2136.22    98.9 2135.85   118.7  2133.9   128.7 2133.62   148.6 2133.33
   168.6 2132.87   198.5 2131.72   208.4 2131.09   218.4 2130.09   228.4 2128.46
   238.3 2127.23   244.5 2127.14   248.3 2127.08   258.3 2127.16   259.5 2127.26
   268.2 2128.01   278.2 2129.97   288.2 2133.02   298.1 2136.91   308.1 2141.54
   318.1 2146.73     328 2152.53     338 2158.87   367.9 2179.06   377.9 2184.96
#Mann= 3 , 0 , 0
       0     .08       0   244.5    .045       0   259.5     .08       0
Bank Sta=244.5,259.5
XS Rating Curve= 0 ,0
Exp/Cntr=0.3,0.1

Type RM Length L Ch R = 1 ,71.1    ,74.6,71.1,67.2
XS GIS Cut Line= 4
     2173007.269      264630.168     2173087.978      264730.738
     2173343.123      264843.657     2173588.058      264617.542
#Sta/Elev= 30
       0 2136.04    19.8    2136    49.6 2135.22    69.4 2134.26    89.3 2132.96
   109.1 2131.06   138.9 2127.47   178.8 2121.92   198.7 2119.48   208.7 2118.57
   218.6 2117.98   248.5 2116.71   258.5 2116.78   262.8 2117.03   277.8 2117.91
   328.2 2120.35   358.1 2121.55   378.1 2122.19     408 2122.61   417.8 2123.27
   437.4 2124.17   466.8 2124.87   496.2 2125.18   525.6 2125.22   653.1 2123.78
   662.9  2124.1   672.7 2126.78   682.5 2130.76   702.1 2139.71   741.3  2158.1
#Mann= 3 , 0 , 0
       0      .1       0   262.8    .045       0   277.8      .1       0
Bank Sta=262.8,277.8
XS Rating Curve= 0 ,0
Exp/Cntr=0.3,0.1

Chan Stop Cuts=-1
Use User Specified Reach Order=0
Composite Channel Slope=5